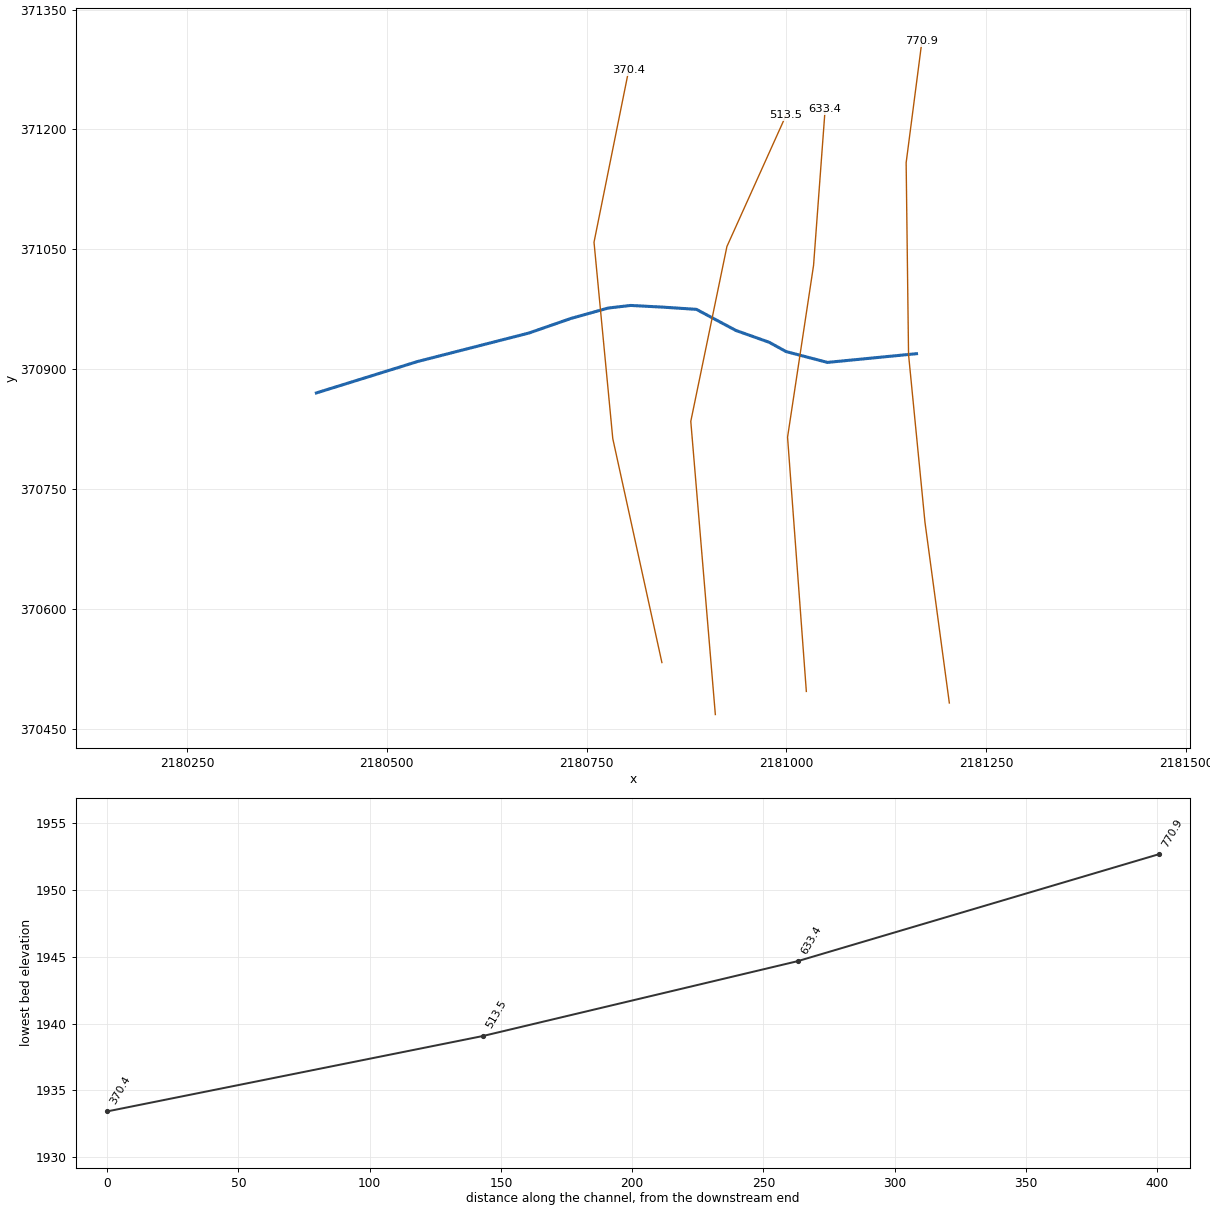
--- KincaidRun.prj (project) ---

Proj Title=KincaidRun
Current Plan=p01
Geom File=g01
Flow File=f01
Plan File=p01
DSS Export Rating Curves=0
DSS Export Rating Curve Sorted=0
DSS Export Volume Flow Curves=0
DXF OffsetX=0
DXF OffsetY=0
DXF ScaleX=0
DXF ScaleY=0

--- KincaidRun.p01 (plan) ---

Plan Title=Floodplain
Program Version=4.00
Geom File=g01
Flow File=f01
K Sum by GR=0
Std Step Tol=0.01
Critical Tol=0.01
Num of Std Step Trials=20
Max Error Tol=0.3
Flow Tol Ratio=0.001
Split Flow NTrial=30
Split Flow Tol=0.02
Split Flow Ratio=0.02
Log Output Level=0
Friction Slope Method=1
Unsteady Friction Slope Method=2
Unsteady Bridges Friction Slope Method=1
Global Log Level=0
CheckData=False
Run HTab=0
Run UNet=0
Run PostProcess=0
UNET Theta=0
UNET Theta Warmup=0
UNET ZTol=0
UNET ZSATol=0
UNET MxIter=0
UNET MaxInSteps=0
UNET DtIC=0
UNET DtMin=0
UNET MaxCRTS=0
UNET WFStab=0
UNET SFStab=0
UNET WFX=0
UNET SFX=0
UNET DSS MLevel=0
UNET DZMax Abort=0
UNET Convert EG Bridges=0
UNET Use Existing IB Tables=0
UNET Froude Limit=0
UNET Froude Power=0
Write IC File=0
Echo Input=False
Echo Output=False
Write Detailed=0

--- KincaidRun.f01 (steady flow) ---

Flow Title=NFF Regression Equation
Program Version=4.00
Number of Profiles=1
Profile Names=P100yr
River Rch & RM=KincaidRun,Main      ,770.9
517.1070
Boundary for River Rch & Prof#=KincaidRun,Main      ,1
Up Type=0
Dn Type=3
Dn Slope=0.015

--- KincaidRun.g01 (geometry) ---

Geom Title=USGS 10m DEM
Program Version=4.00

River Reach=KincaidRun      ,Main
Reach XY= 13
     2181162.747      370919.461     2181051.325      370908.554
     2180999.528      370922.113     2180978.549      370933.688
     2180936.857       370948.51       2180887.4      370974.922
     2180846.145      370977.668     2180805.109      370979.827
     2180777.032      370976.588     2180730.597      370963.629
     2180677.682      370945.271     2180538.375      370909.634
     2180411.921      370870.365

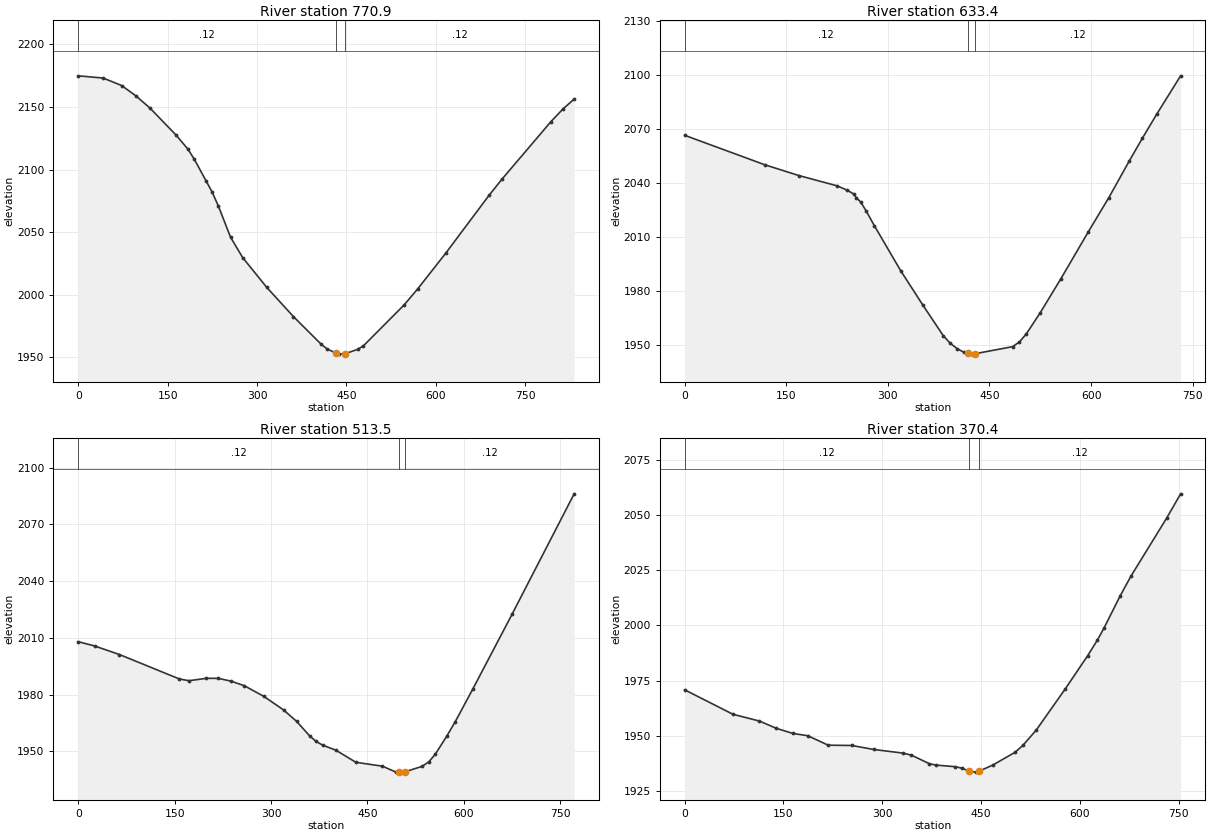
Type RM Length L Ch R = 1 ,770.9   ,143.8,137.5,133.3
XS GIS Cut Line= 5
     2181203.833      370482.435     2181173.347      370708.535
     2181152.794      370918.487     2181149.791      371158.354
     2181169.496      371310.135
#Sta/Elev= 30
       0 2174.79    41.8 2173.02    72.8 2167.06    96.4 2158.93     120 2149.24
     164  2127.6   184.4 2116.08   194.6 2108.33   214.2 2091.23   224.6 2082.08
   235.3 2070.68   255.6 2045.97   275.9 2029.75     316 2006.13     361 1982.67
   407.8  1960.5     418  1956.7   433.3 1953.32   438.2 1952.69   448.4 1953.12
   468.6 1956.44   478.6 1959.39   546.6 1991.87   569.5 2004.74   616.4 2033.14
   689.2  2079.4   711.6 2092.71   792.6 2137.99     813 2148.24     832 2156.24
#Mann= 3 , 0 , 0
       0     .12       0   433.3     .05       0   448.4     .12       0
Bank Sta=433.3,448.4
XS Rating Curve= 0 ,0
Exp/Cntr=0.3,0.1

Type RM Length L Ch R = 1 ,633.4   ,121.1,119.9,118.8
XS GIS Cut Line= 4
      2181024.92      370496.892     2181001.426       370814.96
     2181033.956      371030.018     2181048.414      371225.196
#Sta/Elev= 30
       0 2066.25   118.1  2049.9   168.4 2043.91     225 2038.18   239.6  2035.8
   249.8  2033.6   253.3 2031.64   259.9 2029.14   267.6 2024.46   280.1 2016.01
   318.9 1991.03   351.3 1972.12   381.9 1954.86   392.2 1950.65   402.4 1947.71
   412.6 1945.62   417.8 1945.06   422.8 1944.68     428 1944.86   484.1 1948.82
   494.3 1951.48   504.5 1955.97   524.9 1967.66   555.4 1986.55   595.9 2012.61
   626.3 2031.68   656.6 2052.14   675.8 2064.67   697.1 2078.09   732.2 2099.29
#Mann= 3 , 0 , 0
       0     .12       0   417.8     .05       0     428     .12       0
Bank Sta=417.8,428
XS Rating Curve= 0 ,0
Exp/Cntr=0.3,0.1

Type RM Length L Ch R = 1 ,513.5   ,135.7,143.1,150.5
XS GIS Cut Line= 4
     2180911.066      370467.977     2180880.344       370834.84
     2180925.524      371053.512     2180999.619      371217.967
#Sta/Elev= 30
       0 2008.02    25.7 2005.73    64.2 2001.22   157.4 1988.31   172.5 1987.38
   199.3 1988.65   218.2 1988.62     238 1987.14   258.7 1984.71   289.1 1979.06
   319.5 1971.96   339.8 1965.93     360 1958.28   370.2  1955.3   380.5 1953.32
   401.1 1950.64   432.1 1944.27   473.4 1942.21   493.9 1939.16   499.3 1939.18
   504.2 1939.07   509.3 1939.32   535.2 1942.12   545.5 1944.47   555.8 1948.56
   573.9 1958.29   586.7 1965.69   613.8 1982.81     675  2022.4   771.8 2086.16
#Mann= 3 , 0 , 0
       0     .12       0   499.3     .05       0   509.3     .12       0
Bank Sta=499.3,509.3
XS Rating Curve= 0 ,0
Exp/Cntr=0.3,0.1

Type RM Length L Ch R = 1 ,370.4   ,365.2,370.4,375.6
XS GIS Cut Line= 4
     2180844.199      370533.036     2180782.754      370813.153
     2180759.261      371058.933     2180802.634      371273.991
#Sta/Elev= 30
       0 1970.79    73.3 1959.68   113.5 1956.61   138.9 1953.33   164.4 1950.98
     187 1949.93     218 1945.65   253.8 1945.52   286.8 1943.71   330.9 1942.08
   344.4 1941.12   371.5 1937.25   381.6 1936.62   411.2 1935.87   421.6 1935.16
   432.3 1933.83   442.5 1933.42   447.5  1933.9   467.9 1936.64   501.4 1942.36
   513.5 1945.54   533.7 1952.44   577.6 1971.06   611.9 1986.25   626.5 1993.24
   636.8 1998.84   661.3 2013.43     678 2022.56   731.9 2048.74   753.1 2059.76
#Mann= 3 , 0 , 0
       0     .12       0   432.3     .05       0   447.5     .12       0
Bank Sta=432.3,447.5
XS Rating Curve= 0 ,0
Exp/Cntr=0.3,0.1

Chan Stop Cuts=-1
Use User Specified Reach Order=0